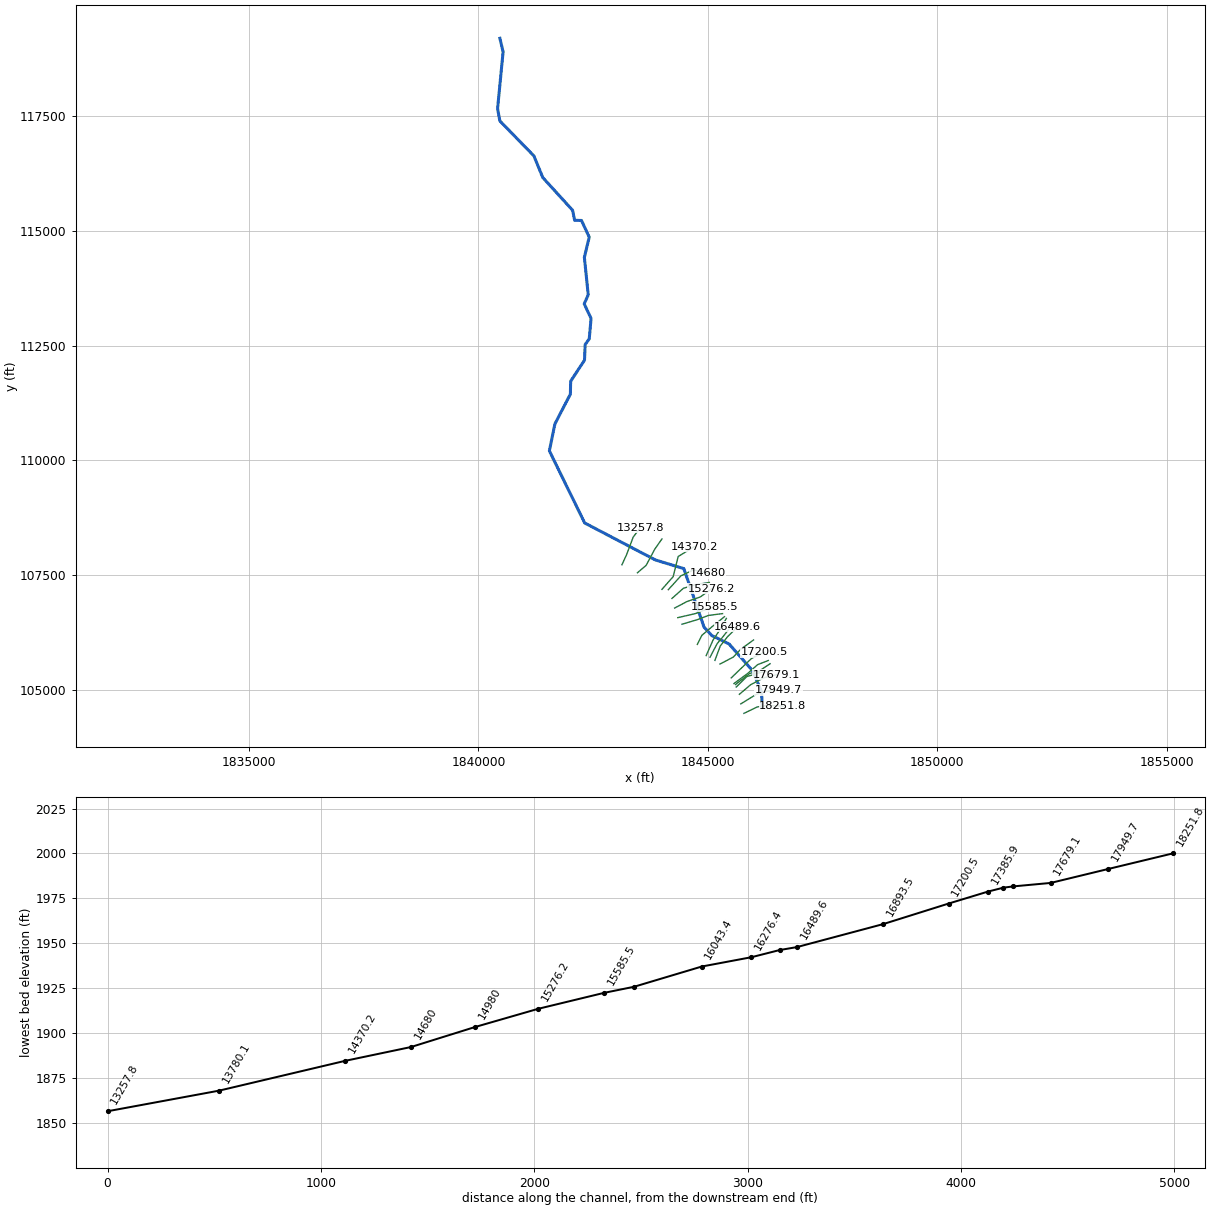
--- Tug Fork.prj (project) ---

Proj Title=Tug Fork
Current Plan=p01
Default Exp/Contr=0,0
English Units
Geom File=g01
Flow File=f01
Plan File=p01
BEGIN DESCRIPTION:
END DESCRIPTION:
DSS Export Rating Curves= 0
DSS Export Rating Curve Sorted= 0
DSS Export Volume Flow Curves= 0
DXF OffsetX= 0
DXF OffsetY= 0
DXF ScaleX= 0
DXF ScaleY= 0

--- Tug Fork.p01 (plan) ---

Plan Title=Floodplain
Program Version=4.00
Geom File=g01
Flow File=f01
K Sum by GR=0
Std Step Tol=0.01
Critical Tol=0.01
Num of Std Step Trials=20
Max Error Tol=0.3
Flow Tol Ratio=0.001
Split Flow NTrial=30
Split Flow Tol=0.02
Split Flow Ratio=0.02
Log Output Level=0
Friction Slope Method=1
Unsteady Friction Slope Method=2
Unsteady Bridges Friction Slope Method=1
Global Log Level=0
CheckData=False
Run HTab=0
Run UNet=0
Run PostProcess=0
UNET Theta=0
UNET Theta Warmup=0
UNET ZTol=0
UNET ZSATol=0
UNET MxIter=0
UNET MaxInSteps=0
UNET DtIC=0
UNET DtMin=0
UNET MaxCRTS=0
UNET WFStab=0
UNET SFStab=0
UNET WFX=0
UNET SFX=0
UNET DSS MLevel=0
UNET DZMax Abort=0
UNET Convert EG Bridges=0
UNET Use Existing IB Tables=0
UNET Froude Limit=0
UNET Froude Power=0
Write IC File=0
Echo Input=False
Echo Output=False
Write Detailed=0

--- Tug Fork.f01 (steady flow) ---

Flow Title=NFF Regression Equation
Program Version=4.00
Number of Profiles=1
Profile Names=P100yr
River Rch & RM=Tug Fork,Main      ,18251.8
622.6288
River Rch & RM=Tug Fork,Main      ,17385.9
800.0498
River Rch & RM=Tug Fork,Main      ,16893.5
809.8520
River Rch & RM=Tug Fork,Main      ,14680
898.3364
River Rch & RM=Tug Fork,Main      ,14370.2
1245.420
Boundary for River Rch & Prof#=Tug Fork,Main      ,1
Up Type=0
Dn Type=3
Dn Slope=0.024965

--- Tug Fork.g01 (geometry) ---

Geom Title=USGS 10m DEM
Program Version=4.00

River Reach=Tug Fork        ,Main
Reach XY= 30
     1846181.438      104638.702      1846173.82      104955.955
     1845976.285      105417.958     1845462.586      106003.488
     1845086.563      106185.786     1844916.136      106371.779
     1844476.735      107643.797     1843856.578      107832.454
     1842316.024       108637.83     1841546.027      110208.078
     1841666.281      110794.931     1842004.213      111445.218
     1842009.382       111723.29     1842311.943      112184.749
     1842326.091      112524.857     1842414.791      112647.296
     1842454.516      113091.885     1842305.413      113410.771
     1842392.481      113607.762     1842308.678      114424.021
     1842414.791      114863.169     1842245.554      115226.676
     1842096.994      115228.309     1842051.828      115448.699
      1841402.63      116160.477     1841208.904      116631.731
     1840466.652      117394.661     1840416.967      117661.636
     1840537.395      118897.667     1840467.872      119192.773

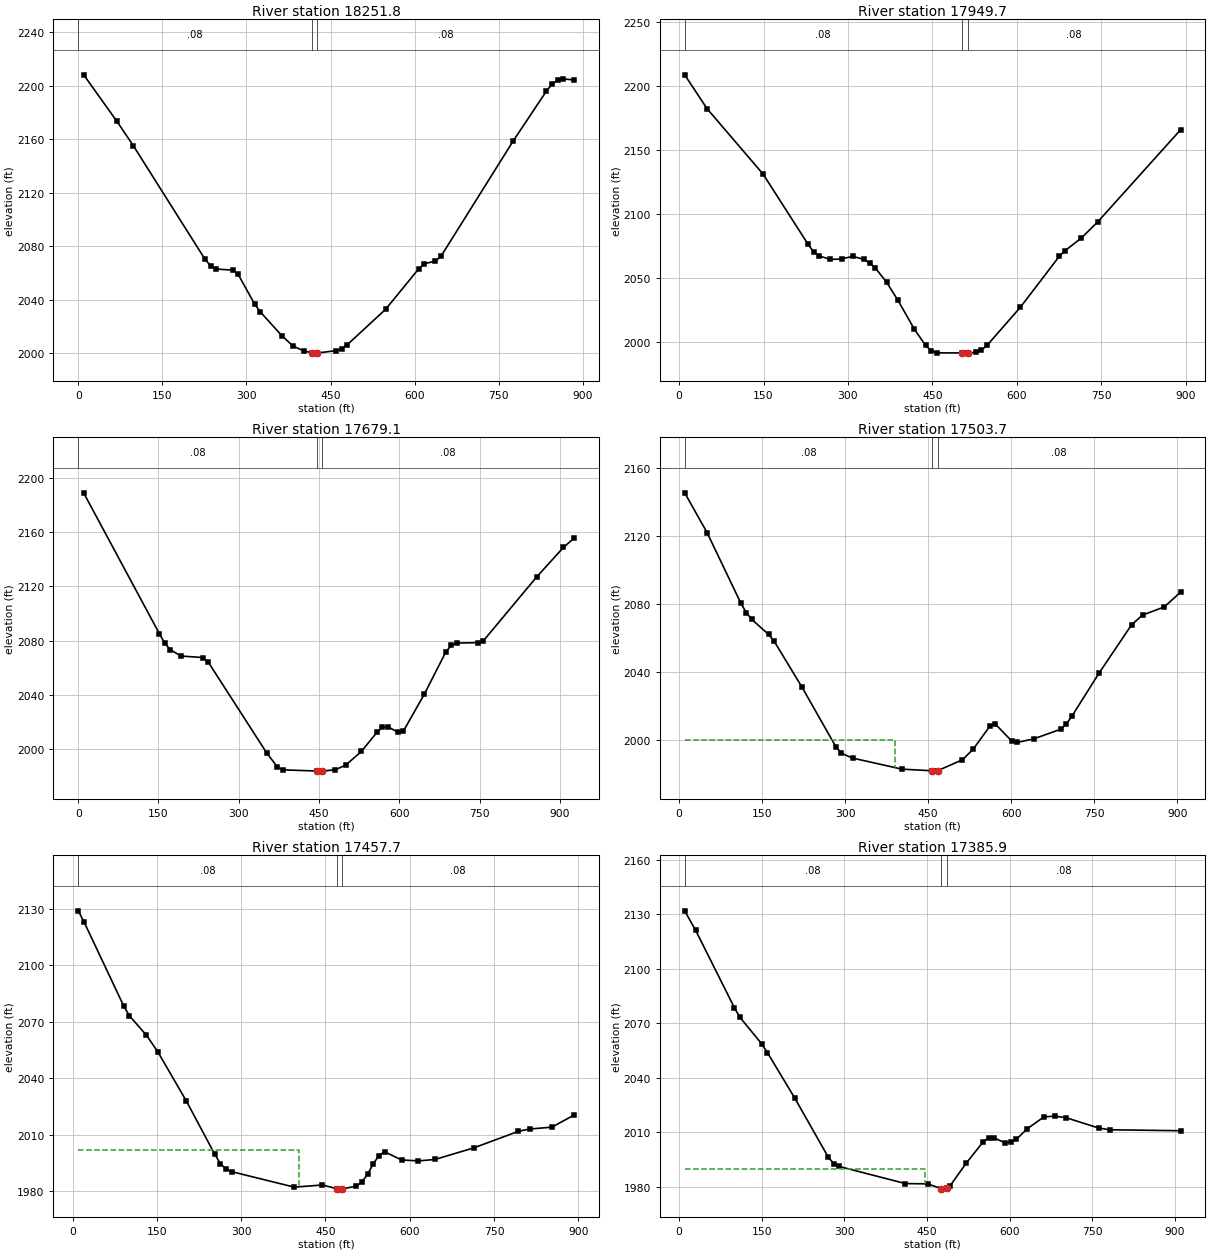
Type RM Length L Ch R = 1 ,18251.8 ,298.9,302.1,305.4
XS GIS Cut Line= 4
     1845785.863      104491.239      1846078.19      104632.431
     1846318.812      104666.237     1846635.309      104648.702
#Sta/Elev= 30
     9.8 2208.27    68.9 2173.53    98.4 2155.19   226.3 2070.18   236.1 2065.48
   245.9 2062.99   275.5 2062.13   285.3 2058.97   314.8 2036.64   324.6 2031.01
   363.5 2012.97     383  2005.4   402.4 2001.72   416.8  2000.3   421.8 2000.05
   426.8 2000.17   460.7 2001.93   470.4 2003.25   480.1 2006.42   548.2 2032.79
   607.2 2063.08   617.2 2066.91     637 2068.93   646.9  2072.4   775.6 2158.61
   835.1  2196.1     845 2201.17   854.9 2204.31   864.8  2205.2   884.6 2204.48
#Mann= 3 , 0 , 0
       0     .08       0   416.8    .045       0   426.8     .08       0
Bank Sta=416.8,426.8
XS Rating Curve= 0 ,0
Exp/Cntr=0.3,0.1

Type RM Length L Ch R = 1 ,17949.7 ,267,270.6,274.2
XS GIS Cut Line= 4
     1845718.002      104697.807     1846048.609       104901.64
     1846284.757      104976.213     1846538.305       105001.07
#Sta/Elev= 30
      10 2208.78    49.8  2182.3   149.4 2131.15   229.1 2076.44     239 2070.52
     249 2067.33   268.9 2064.55   288.8 2065.01   308.7    2067   328.6 2064.59
   338.6 2061.67   348.6 2057.91   368.5 2046.81   388.4 2032.92   418.1    2010
   437.9  1997.4   447.8 1993.25   457.7  1991.6   502.3 1991.57  507.29 1991.41
   512.3 1991.44   527.1 1991.97     537  1993.8   546.9 1997.41   606.3 2027.31
   675.2 2066.94     685 2071.23   714.4 2081.27   743.8 2094.03   890.8 2165.89
#Mann= 3 , 0 , 0
      10     .08       0   502.3    .045       0   512.3     .08       0
Bank Sta=502.3,512.3
XS Rating Curve= 0 ,0
Exp/Cntr=0.3,0.1

Type RM Length L Ch R = 1 ,17679.1 ,179.1,175.4,171.7
XS GIS Cut Line= 4
     1845686.733      104906.247     1845933.021      105115.664
     1846219.381      105266.799      1846491.76      105330.549
#Sta/Elev= 30
    10.1 2189.15   151.5 2085.24   161.6 2078.25   171.7 2073.34     192 2068.63
   232.4 2067.52   242.5 2064.44   352.7 1996.79   372.3 1986.73   382.2 1984.56
   445.8  1983.7   450.8 1983.62   455.8 1983.63   480.3 1984.63   499.9 1988.03
   529.3 1998.21   558.8 2012.52   568.6 2015.97   578.4 2016.49     598 2012.19
   607.8 2013.24   647.1 2040.66     687 2071.62     697 2076.41     707  2078.2
     747  2078.5     757 2079.79   856.9  2127.1   906.8 2148.81   926.8 2155.76
#Mann= 3 , 0 , 0
       0     .08       0   445.8    .045       0   455.8     .08       0
Bank Sta=445.8,455.8
XS Rating Curve= 0 ,0
Exp/Cntr=0.3,0.1

Type RM Length L Ch R = 1 ,17503.7 ,47.8,46,44.2
XS GIS Cut Line= 4
     1845618.571        105065.7     1845849.748      105291.905
     1846134.015       105379.71     1846416.503      105418.679
#Sta/Elev= 30
    10.1 2145.18    50.5 2121.86   111.2 2080.59   121.3 2074.87   131.4  2070.8
   161.7 2061.98   171.8 2057.97   222.4 2030.82     283 1996.15   293.1 1992.21
   313.3 1989.37   402.8 1982.84   457.3 1981.91   462.3 1981.69   467.3 1981.98
   511.9 1988.34   531.7 1994.71   561.5 2008.11   571.4  2009.3   601.1 1999.33
     611 1998.56   640.6 2000.62   689.8 2006.34   699.6 2009.42   709.5 2013.87
   758.6 2039.19   817.6  2067.7   837.3 2073.37   876.6 2078.16   906.1 2086.85
#Mann= 3 , 0 , 0
    10.1     .08       0   457.3    .045       0   467.3     .08       0
#XS Ineff= 2 , 0
          389.59 2000.08
Permanent Ineff=
       F       F
Bank Sta=457.3,467.3
XS Rating Curve= 0 ,0
Exp/Cntr=0.3,0.1

Type RM Length L Ch R = 1 ,17457.7 ,61.5,71.8,82.2
XS GIS Cut Line= 4
     1845602.228      105119.466     1845912.863      105362.572
     1846108.698      105407.592     1846356.306      105571.913
#Sta/Elev= 30
    10.1 2128.97    20.2 2123.24      91 2078.41   101.1 2073.19   131.5 2062.83
   151.7 2054.03   202.3 2027.96   252.9 1999.61     263 1994.58   273.1 1991.57
   283.2 1990.28   394.5 1982.05   444.7 1983.18   469.8 1981.28   474.8 1980.99
   479.8  1981.1     505 1982.58     515 1984.73   525.1 1988.99   535.1 1994.39
   545.2 1998.86   555.2 2000.85   585.4 1996.51   615.2    1996   644.9 1996.76
   714.3 2002.95   793.5 2011.75   813.3 2012.94   852.9 2013.94   892.6 2020.39
#Mann= 3 , 0 , 0
    10.1     .08       0   469.8    .045       0   479.8     .08       0
#XS Ineff= 2 , 0
          403.42 2001.83
Permanent Ineff=
       F       F
Bank Sta=469.8,479.8
XS Rating Curve= 0 ,0
Exp/Cntr=0.3,0.1

Type RM Length L Ch R = 1 ,17385.9 ,184.3,185.4,186.5
XS GIS Cut Line= 4
     1845568.989      105140.529     1845874.738      105366.734
     1846086.029      105553.167     1846317.205      105642.654
#Sta/Elev= 30
      10 2131.88      30  2121.1   100.1 2078.68   110.1 2073.37   150.1  2058.6
   160.1 2053.93   210.2 2028.68   270.2 1996.61   280.2  1992.9   290.3  1991.3
   410.5 1981.89   450.8 1981.72     476 1979.08     481 1978.83     486 1979.59
     491 1980.36   521.2 1993.22   551.4 2004.73   561.5 2007.13   571.5 2007.03
   591.7 2004.21   601.7  2004.6   611.8 2006.19   631.9 2012.13   662.1 2018.56
   681.9 2018.97   701.8 2018.14   761.3 2012.44   781.1 2011.48     910 2010.94
#Mann= 3 , 0 , 0
      10     .08       0     476    .045       0     486     .08       0
#XS Ineff= 2 , 0
          445.54 1989.94
Permanent Ineff=
       F       F
Bank Sta=476,486
XS Rating Curve= 0 ,0
Exp/Cntr=0.3,0.1

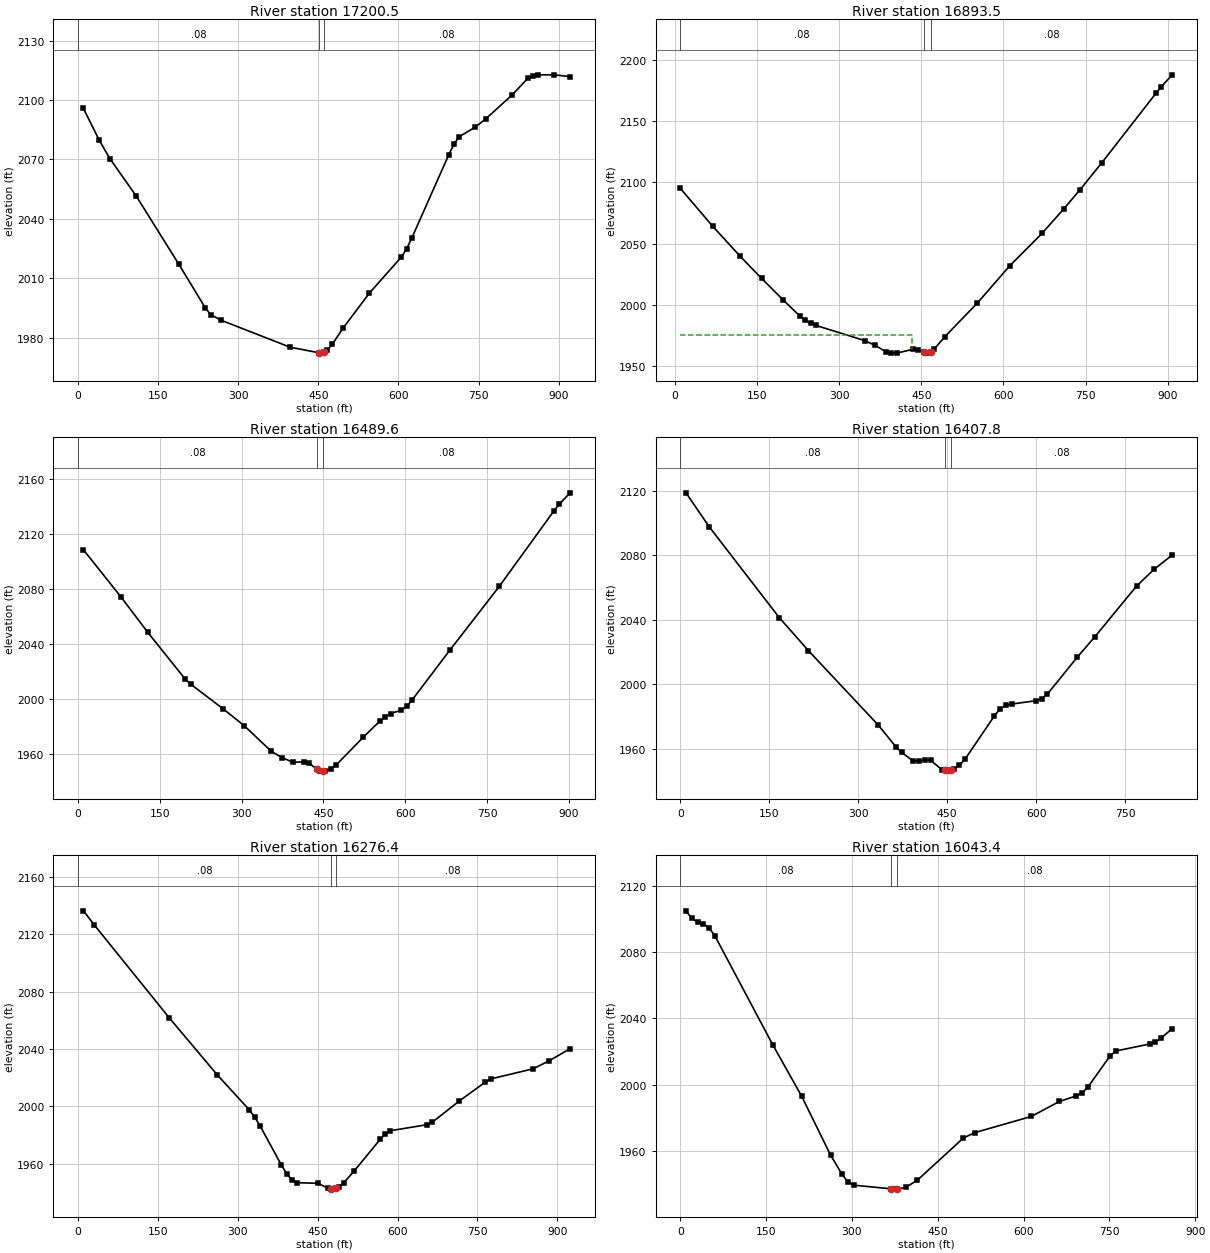
Type RM Length L Ch R = 1 ,17200.5 ,306.2,307,307.8
XS GIS Cut Line= 4
     1845509.755      105264.261     1845752.803      105498.224
      1845954.15      105689.628     1846229.889      105822.474
#Sta/Elev= 30
     9.9 2095.83    39.7  2079.7    59.5 2070.43   109.1 2051.42   188.5 2017.14
   238.1 1995.09   248.1 1991.62   267.9 1988.75   396.9 1975.15   451.4 1972.31
   456.4 1972.14   461.4 1972.83   466.3  1973.5   476.3  1976.7   496.1 1984.75
   545.7  2002.5   605.2 2020.62   615.2 2024.75     625 2030.31   694.2 2072.37
     704 2077.74   713.9 2081.47   743.5 2086.23   763.3 2090.44   812.6 2102.48
   842.3 2110.95   852.1 2112.34     862 2112.69   891.6 2112.68   921.2 2111.79
#Mann= 3 , 0 , 0
       0     .08       0   451.4    .045       0   461.4     .08       0
Bank Sta=451.4,461.4
XS Rating Curve= 0 ,0
Exp/Cntr=0.3,0.1

Type RM Length L Ch R = 1 ,16893.5 ,401.9,403.9,405.9
XS GIS Cut Line= 4
      1845264.03      105565.513     1845553.941      105716.971
     1845722.973      105893.461     1845996.408      106089.837
#Sta/Elev= 30
     9.9 2095.28    69.4 2064.17   118.9    2040   158.6 2021.62   198.2 2003.94
     228 1991.15   237.9 1987.61   247.8 1985.06   257.7 1983.32   346.6 1970.95
   366.2 1966.99   385.7  1961.7   395.5  1960.7   405.3 1960.71   434.6 1963.82
   444.4    1963   454.2 1961.41   463.9 1961.01  467.28 1961.65   473.7 1963.99
   493.3 1974.25   551.9 2001.33   611.1 2031.79   670.5 2058.47   710.1  2078.4
   739.8 2094.05   779.4 2115.96   878.4 2172.78   888.3 2178.22   908.1 2187.85
#Mann= 3 , 0 , 0
     9.9     .08       0   454.2    .045       0  467.28     .08       0
#XS Ineff= 2 , 0
          432.19 1975.62
Permanent Ineff=
       F       F
Bank Sta=454.2,467.28
XS Rating Curve= 0 ,0
Exp/Cntr=0.3,0.1

Type RM Length L Ch R = 1 ,16489.6 ,82.5,81.8,81
XS GIS Cut Line= 4
     1845153.733      105644.884     1845270.564      105958.091
     1845429.653      106161.924     1845650.886      106378.186
#Sta/Elev= 30
     9.8 2108.75    78.7 2074.49   127.8 2048.79   196.6 2014.73   206.5 2011.08
   265.5 1993.35   304.8 1980.86   354.2  1962.4   374.1 1957.69     394 1954.43
   413.8 1954.59   423.8 1953.61   438.7 1949.16   443.7 1947.92   448.7 1947.97
   453.6 1948.01   463.6 1949.56   473.5 1952.39   523.2 1972.61   553.1 1984.11
     563 1987.44     573 1989.77   592.9 1992.15   602.8 1995.01   612.8  1999.7
   682.7 2036.24   772.5 2082.14   872.3 2136.76   882.3 2141.67   902.2 2150.06
#Mann= 3 , 0 , 0
       0     .08       0   438.7    .045       0   448.7     .08       0
Bank Sta=438.7,448.7
XS Rating Curve= 0 ,0
Exp/Cntr=0.3,0.1

Type RM Length L Ch R = 1 ,16407.8 ,129.2,131.4,133.7
XS GIS Cut Line= 4
     1845047.396      105714.227     1845202.542      106010.019
     1845334.489      106166.615     1845512.834      106395.708
#Sta/Elev= 30
     9.8  2118.8    49.1 2097.63     167 2041.41   216.1 2020.95     334 1974.69
   363.3 1961.42     373 1957.88   392.5  1952.6   402.3  1952.4     412 1953.31
   421.8 1952.98   441.3 1947.05     446 1946.66     451 1946.25     456  1946.8
   460.8 1947.33   470.5 1949.83   480.3  1953.8     529 1980.24   538.8  1984.8
   548.8 1986.97   558.8 1987.84   598.9 1989.88   608.9 1991.15   618.9 1994.08
   668.9  2016.8     699 2029.65     769 2060.99   799.1 2071.54   829.1 2080.22
#Mann= 3 , 0 , 0
       0     .08       0     446    .045       0     456     .08       0
Bank Sta=446,456
XS Rating Curve= 0 ,0
Exp/Cntr=0.3,0.1

Type RM Length L Ch R = 1 ,16276.4 ,238.8,233,227.2
XS GIS Cut Line= 4
     1844963.493       105749.57      1845113.96      106089.837
     1845260.621      106308.584     1845402.952      106559.354
#Sta/Elev= 30
    10.1 2136.24    30.2 2126.55   170.9 2061.84   261.4 2021.92   321.8 1997.44
   331.8 1992.39   341.9 1986.34   381.8 1959.07   391.6 1953.16   401.3 1948.68
   411.1 1946.78   450.1 1946.35   469.6 1942.86   474.3 1942.58   479.3 1942.29
   484.3 1943.03   489.1 1943.74   498.9 1946.69   518.4 1954.88   567.1 1976.88
   576.9 1980.63   586.6 1983.01   655.3  1987.2   665.2 1988.91     715 2003.47
   764.7 2016.87   774.6 2019.05   854.2 2026.13     884 2031.59   923.8 2040.14
#Mann= 3 , 0 , 0
       0     .08       0   474.3    .045       0   484.3     .08       0
Bank Sta=474.3,484.3
XS Rating Curve= 0 ,0
Exp/Cntr=0.3,0.1

Type RM Length L Ch R = 1 ,16043.4 ,324.7,318,311.3
XS GIS Cut Line= 4
     1844770.924      105992.892     1844870.355      106191.753
     1845094.074      106380.671     1845362.537      106596.933
#Sta/Elev= 30
    10.1 2104.83    20.2 2100.24    30.3  2098.1    40.4 2097.01    50.5 2094.57
    60.6 2089.76   161.7 2024.15   212.2 1993.15   262.7 1957.66   282.9    1946
     293 1941.47   303.1 1939.48   368.8 1937.29   373.8  1937.1   378.8 1937.13
     394 1938.13   414.2 1942.41     495 1967.91   515.1 1971.18   613.6  1980.9
   662.9 1989.95   692.4 1993.31   702.3 1995.11   712.1 1998.38   751.5 2017.49
   761.4 2020.37   820.5 2024.55   830.3 2025.78   840.2 2027.99   859.9 2033.88
#Mann= 3 , 0 , 0
       0     .08       0   368.8    .045       0   378.8     .08       0
Bank Sta=368.8,378.8
XS Rating Curve= 0 ,0
Exp/Cntr=0.3,0.1

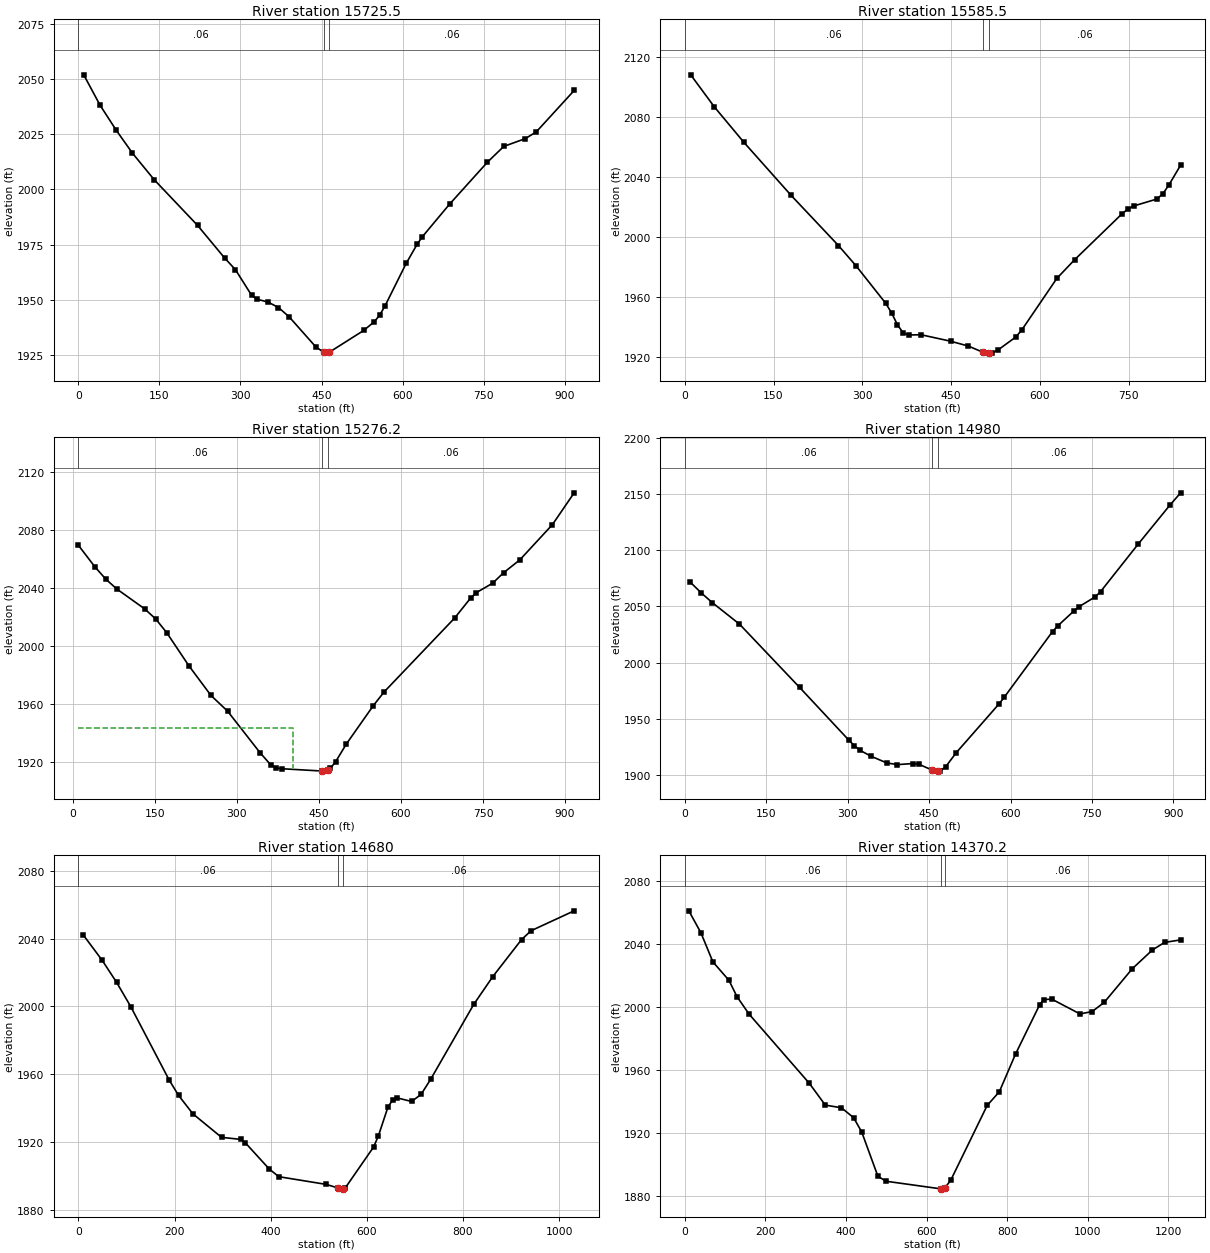
Type RM Length L Ch R = 1 ,15725.5 ,139.9,140,140.1
XS GIS Cut Line= 4
     1844436.854      106432.772     1844763.467      106529.817
     1845012.044      106624.277     1845320.279      106664.049
#Sta/Elev= 30
      10 2051.97    40.1 2038.24    70.1 2026.86   100.2 2016.45   140.3 2004.44
   220.5 1983.75   270.6 1968.96   290.6 1963.68   320.7    1952   330.7 1950.25
   350.6    1949   370.3  1946.5     390 1942.29   439.2  1928.7   453.9 1926.22
   458.9 1925.82   463.9 1926.16   527.9 1936.08   547.6 1940.05   557.4 1942.97
   567.2  1947.1   606.6  1966.5   626.7 1975.09   636.7 1978.63   686.8 1993.32
     757 2012.39   787.1 2019.51   827.2 2023.08   847.3  2026.1   917.4 2044.88
#Mann= 3 , 0 , 0
       0     .06       0   453.9    .045       0   463.9     .06       0
Bank Sta=453.9,463.9
XS Rating Curve= 0 ,0
Exp/Cntr=0.3,0.1

Type RM Length L Ch R = 1 ,15585.5 ,310,309.3,308.5
XS GIS Cut Line= 4
     1844345.536      106576.022     1844724.987      106663.479
     1844911.186      106735.419     1845146.756      106815.823
#Sta/Elev= 30
      10 2108.24    49.9 2086.85    99.8 2063.21   179.7 2027.75   259.6  1994.3
   289.6 1980.64   339.5 1955.73   349.5 1949.29   359.4 1941.33   369.4 1935.78
   379.4 1934.58   399.4 1934.71   449.3 1930.39   479.2 1927.16   504.2 1922.98
   509.2 1922.45   514.2 1922.54   519.1 1922.62   529.1  1924.5   559.1 1933.13
   569.1  1937.7   628.8 1972.38   658.7 1984.78   738.4 2015.27   748.3 2018.49
   758.3 2020.65   798.1 2025.36   808.1 2028.99     818 2034.64   837.9 2047.96
#Mann= 3 , 0 , 0
       0     .06       0   504.2    .045       0   514.2     .06       0
Bank Sta=504.2,514.2
XS Rating Curve= 0 ,0
Exp/Cntr=0.3,0.1

Type RM Length L Ch R = 1 ,15276.2 ,296.9,296.2,295.5
XS GIS Cut Line= 4
     1844276.851      106785.432      1844545.03      106926.608
     1844834.001      107026.039     1845084.141      107205.645
#Sta/Elev= 30
    10.1 2069.43    40.4 2054.47    60.6 2045.88    80.8 2039.11   131.3 2025.51
   151.5 2018.56   171.7 2009.08   212.1  1986.3   252.6 1965.77   282.9 1954.97
   342.5 1926.18   362.2 1917.76   372.1 1915.78   381.9 1915.22   455.8 1913.62
   460.8 1913.56   465.8 1914.48   470.7 1915.38   480.5 1920.07   500.2 1932.32
   549.5  1958.8   569.2 1968.21   698.1 2019.18   727.9 2033.21   737.8  2036.7
   767.6 2043.21   787.5 2050.41   817.3 2059.31   876.9 2083.64   916.6 2105.55
#Mann= 3 , 0 , 0
    10.1     .06       0   455.8    .045       0   465.8     .06       0
#XS Ineff= 2 , 0
           402.3 1943.35
Permanent Ineff=
       F       F
Bank Sta=455.8,465.8
XS Rating Curve= 0 ,0
Exp/Cntr=0.3,0.1

Type RM Length L Ch R = 1 ,14980   ,296.9,299.9,302.8
XS GIS Cut Line= 4
     1844218.773      106994.967      1844467.35      107215.578
     1844722.141      107293.259     1845032.862      107342.974
#Sta/Elev= 30
    10.1 2071.53    30.2 2062.07    50.4 2053.43   100.7 2034.24   211.5 1977.91
   302.1 1931.02   312.2 1926.15   322.3 1922.08   342.2 1916.86   371.8 1910.77
   391.5 1909.21   421.1  1910.2     431 1909.58   455.6 1904.38   460.6 1903.42
   465.6  1903.5   470.5 1903.57   480.3 1907.14   500.1 1919.85     579  1963.3
   588.9 1969.43   677.4 2027.59   687.2 2032.74   716.7 2045.88   726.6 2049.84
   756.1  2058.5   765.9 2063.12   834.7 2105.12   893.7 2140.12   913.4 2151.04
#Mann= 3 , 0 , 0
       0     .06       0   455.6    .045       0   465.6     .06       0
Bank Sta=455.6,465.6
XS Rating Curve= 0 ,0
Exp/Cntr=0.3,0.1

Type RM Length L Ch R = 1 ,14680   ,292.1,309.8,327.6
XS GIS Cut Line= 4
     1844137.986      107184.506      1844411.42      107485.906
     1844687.962      107616.409     1844997.635      107542.624
#Sta/Elev= 30
     9.9 2042.26    49.6 2027.16    79.4 2014.27   109.2 1999.78   188.6 1956.76
   208.4 1947.56   238.2 1936.69   297.8 1922.83   337.5 1921.62   347.4 1919.57
     397 1904.16   416.8 1899.64   515.5 1895.09     540 1892.97     545  1892.3
     550 1892.62   554.9 1892.93   614.1 1917.17     624 1923.68   643.7 1940.53
   653.6 1944.91   663.4 1946.04     693 1943.97   712.7 1948.11   732.6    1957
   822.2 2001.16     862 2017.62   921.6 2039.36   941.5  2044.6  1031.1 2056.34
#Mann= 3 , 0 , 0
       0     .06       0     540    .045       0     550     .06       0
Bank Sta=540,550
XS Rating Curve= 0 ,0
Exp/Cntr=0.3,0.1

Type RM Length L Ch R = 1 ,14370.2 ,595,590.1,585.2
XS GIS Cut Line= 4
     1843999.327      107192.663     1844244.019      107468.428
     1844352.772      107907.321     1844702.333      108120.942
#Sta/Elev= 30
      10 2060.93    39.9 2047.06    69.7 2028.59   109.6 2016.88   129.5 2006.56
   159.4 1995.51   308.9 1951.67   348.7 1937.81   388.8 1936.13   418.9 1929.86
     439 1920.83   479.2 1892.75   499.3 1889.59     635 1884.77     640 1884.58
     645 1885.22   660.1 1890.26   750.5 1937.64   780.6  1946.3   820.8 1970.18
   880.8  2001.5   890.8 2004.73   910.8 2004.97   980.7  1995.6  1010.7 1997.08
  1040.7 2002.86  1110.6 2024.26  1160.6 2036.16  1190.5  2040.9  1230.5 2042.52
#Mann= 3 , 0 , 0
       0     .06       0     635    .045       0     645     .06       0
Bank Sta=635,645
XS Rating Curve= 0 ,0
Exp/Cntr=0.3,0.1

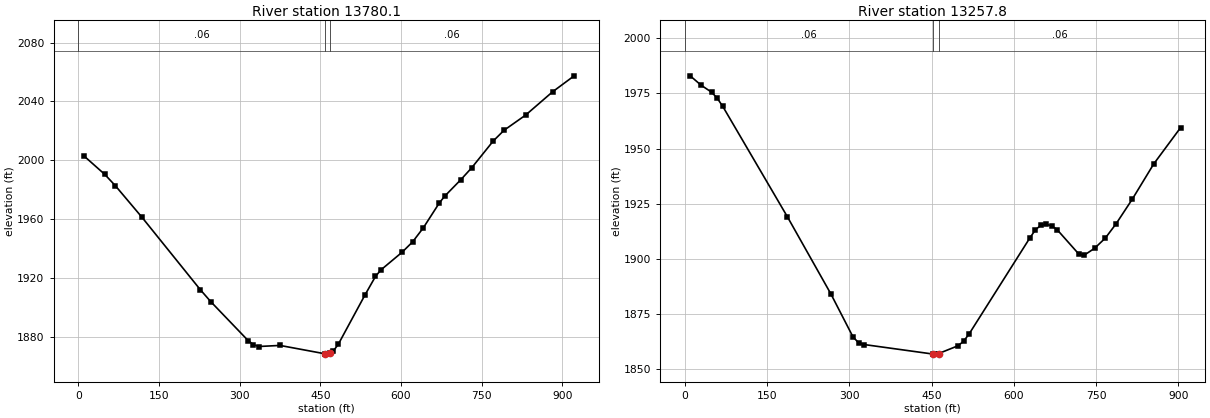
Type RM Length L Ch R = 1 ,13780.1 ,519.7,522.3,524.9
XS GIS Cut Line= 4
     1843465.303      107553.911      1843653.65       107713.12
     1843844.772      108069.883     1844000.356      108291.469
#Sta/Elev= 30
     9.9 2003.08    49.3 1990.28    69.1 1982.52   118.4 1961.12   226.9 1911.84
   246.6 1903.61   315.7 1877.27   325.6 1874.47   335.5 1873.21     375 1873.94
   458.8 1868.24   463.8 1868.02   468.8 1868.97   473.7 1869.89   483.5 1874.75
   532.9 1908.16   552.6 1920.87   562.5 1925.26     602 1937.33   621.7 1944.42
   641.5 1953.93   671.4 1970.93   681.4 1975.53   711.5 1986.79   731.6 1994.85
   771.7 2013.09   791.7 2020.35   831.9 2030.71     882 2046.54   922.1 2057.41
#Mann= 3 , 0 , 0
       0     .06       0   458.8    .045       0   468.8     .06       0
Bank Sta=458.8,468.8
XS Rating Curve= 0 ,0
Exp/Cntr=0.3,0.1

Type RM Length L Ch R = 1 ,13257.8 ,13275.1,13257.8,13239.1
XS GIS Cut Line= 4
     1843127.402      107727.774     1843226.408      107942.277
     1843372.445      108328.852     1843525.477      108532.647
#Sta/Elev= 30
     9.8 1983.03    29.5 1978.82    49.2 1975.53    59.1 1972.86    68.9 1969.28
     187 1919.03   266.5 1883.89   306.8 1864.38   316.9 1861.75     327 1860.93
     453 1856.59     458 1856.57     463 1856.84   498.3 1860.37   508.4  1862.4
   518.5 1865.73   629.3 1909.36   639.4 1913.03   649.5 1915.16   659.3 1915.54
   669.1 1914.88   678.9 1913.17   718.1 1902.18   727.9 1901.45   747.5 1904.68
   767.1 1909.34   786.7 1915.83   816.1 1926.96   855.3 1943.01   904.3 1959.51
#Mann= 3 , 0 , 0
       0     .06       0     453    .045       0     463     .06       0
Bank Sta=453,463
XS Rating Curve= 0 ,0
Exp/Cntr=0.3,0.1

Chan Stop Cuts=-1
Use User Specified Reach Order=0